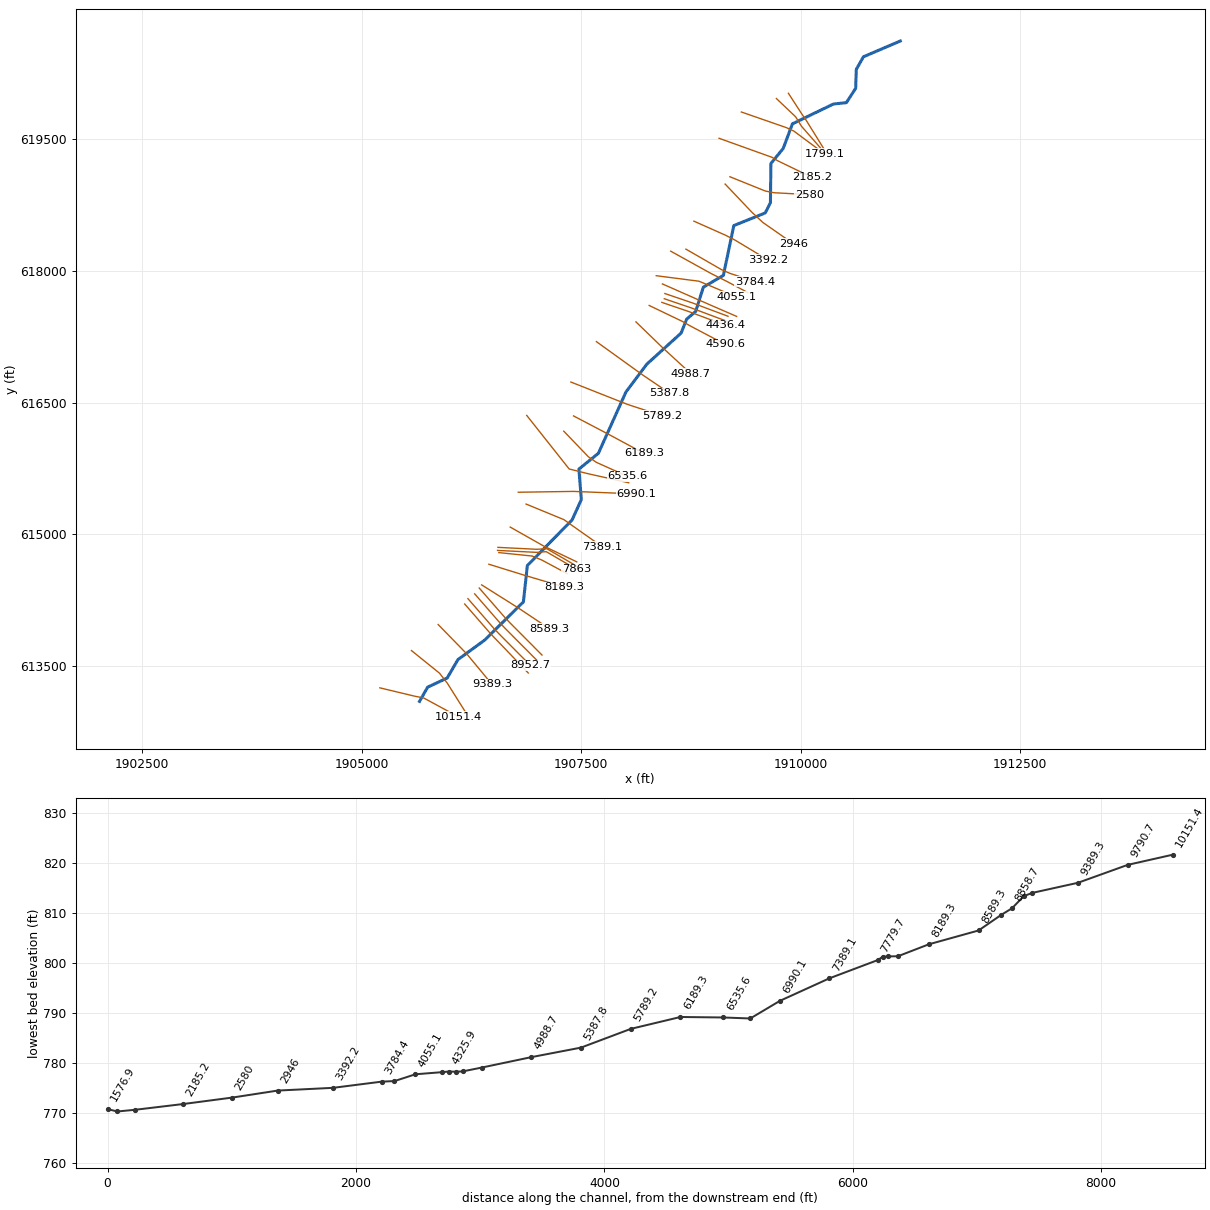
--- CanoeRun.prj (project) ---

Proj Title=CanoeRun
Current Plan=p01
Default Exp/Contr=0,0
English Units
Geom File=g01
Flow File=f01
Plan File=p01
BEGIN DESCRIPTION:
AMEC Environment & Infrastructure, 2013
Projection: NAD 1983 State Plane West Virginia South FIPS 4702 (US Feet)
Vertical Datum: NAVD 1988
END DESCRIPTION:
DSS Export Rating Curves= 0
DSS Export Rating Curve Sorted= 0
DSS Export Volume Flow Curves= 0
DXF OffsetX= 0
DXF OffsetY= 0
DXF ScaleX= 0
DXF ScaleY= 0

--- CanoeRun.p01 (plan) ---

Plan Title=Floodplain
Program Version=4.00
Geom File=g01
Flow File=f01
K Sum by GR=0
Std Step Tol=0.01
Critical Tol=0.01
Num of Std Step Trials=20
Max Error Tol=0.3
Flow Tol Ratio=0.001
Split Flow NTrial=30
Split Flow Tol=0.02
Split Flow Ratio=0.02
Log Output Level=0
Friction Slope Method=1
Unsteady Friction Slope Method=2
Unsteady Bridges Friction Slope Method=1
Global Log Level=0
CheckData=False
Run HTab=0
Run UNet=0
Run PostProcess=0
UNET Theta=0
UNET Theta Warmup=0
UNET ZTol=0
UNET ZSATol=0
UNET MxIter=0
UNET MaxInSteps=0
UNET DtIC=0
UNET DtMin=0
UNET MaxCRTS=0
UNET WFStab=0
UNET SFStab=0
UNET WFX=0
UNET SFX=0
UNET DSS MLevel=0
UNET DZMax Abort=0
UNET Convert EG Bridges=0
UNET Use Existing IB Tables=0
UNET Froude Limit=0
UNET Froude Power=0
Write IC File=0
Echo Input=False
Echo Output=False
Write Detailed=0

--- CanoeRun.f01 (steady flow) ---

Flow Title=NFF Regression Equation
Program Version=4.10
Number of Profiles= 1
Profile Names=P100yr
River Rch & RM=CanoeRun,Main            ,10151.4
894.6682
River Rch & RM=CanoeRun,Main            ,6990.1
985.0382
River Rch & RM=CanoeRun,Main            ,6751.3
1656.889
River Rch & RM=CanoeRun,Main            ,4055.1
1703.109
River Rch & RM=CanoeRun,Main            ,3886.5
1750.889
River Rch & RM=CanoeRun,Main            ,587
1819.284
River Rch & RM=CanoeRun,Main            ,189.5
1825.632
Boundary for River Rch & Prof#=CanoeRun,Main            , 1
Up Type= 0
Dn Type= 3
Dn Slope=0.0007
DSS Import GetInterval= 0
DSS Import GetPeak= 0
DSS Import FillOption= 0

--- CanoeRun.g01 (geometry) ---

Geom Title=USGS 3m DEM
Program Version=4.10

River Reach=CanoeRun        ,Main
Reach XY= 30
     1905659.266      613097.286     1905751.309      613258.804
     1905973.608      613363.014     1906096.911      613573.162
     1906399.097      613793.736     1906841.953      614229.668
     1906886.887      614644.258     1907395.948      615162.309
     1907501.883      615395.035     1907474.086      615742.381
     1907696.384      615923.008     1908010.793      616622.364
     1908246.641      616936.747     1908638.171      617291.756
     1908701.916      617451.363     1908804.381      617538.203
     1908891.211      617814.346     1909119.409      617948.631
     1909238.541      618515.998     1909596.306      618660.156
     1909655.352      618776.519     1909660.664      619222.724
     1909801.223      619394.803      1909905.42       619674.42
     1910372.835      619900.327      1910520.22      619915.843
     1910626.157      620079.099     1910633.099      620294.455
     1910714.722      620438.607     1911134.928      620617.983

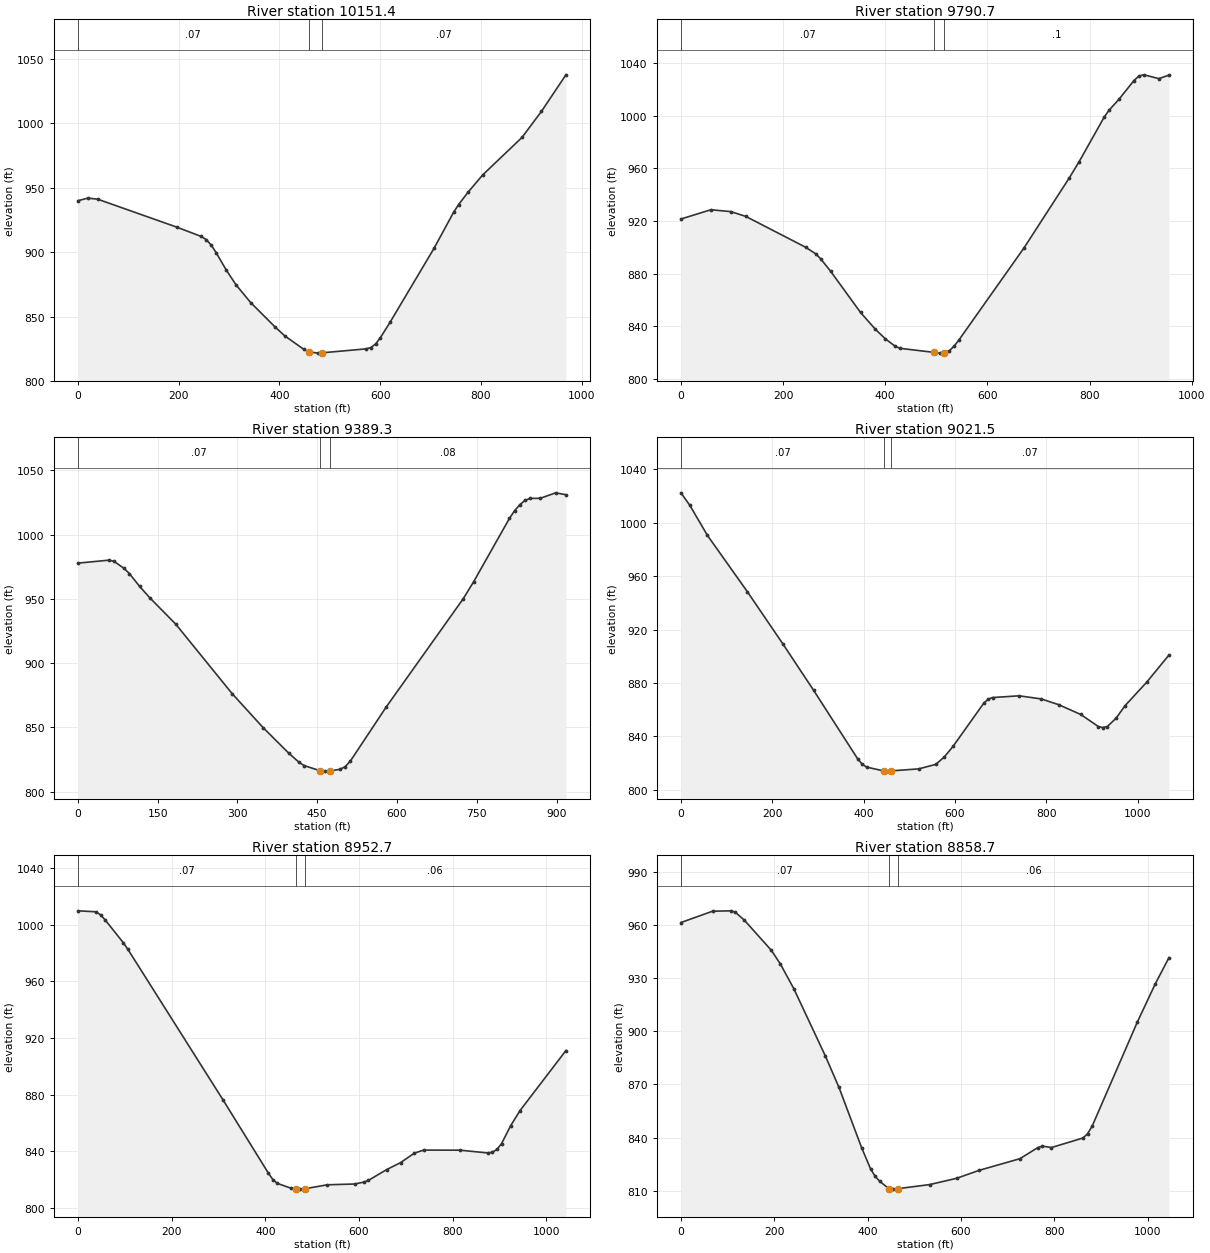
Type RM Length L Ch R = 1 ,10151.4 ,376.6,360.7,344.4
XS GIS Cut Line= 4
     1905206.853      613251.332     1905597.478       613157.69
     1905706.853      613135.555      1906107.27      612918.852
#Sta/Elev= 30
       0  939.89    19.6   941.9    39.2  941.07     196   919.4   244.9  912.12
   254.7  909.66   264.5  905.47   274.3  899.62   293.9  886.38   313.5  874.74
   342.9  860.81   391.9  841.65     411  834.84   448.2  824.54   457.9  822.61
   476.1  821.57   485.4  821.84   571.4  824.86   581.1  825.86   590.8  828.68
   600.5  833.65   619.8   845.7     707  903.06   745.8  930.99   755.5  936.86
   774.8  946.71   803.9  960.12   881.4     989   920.1 1009.27   968.6 1037.61
#Mann= 3 , 0 , 0
       0     .07       0   457.9    .045       0   485.4     .07       0
Bank Sta=457.9,485.4
XS Rating Curve= 0 ,0
Exp/Cntr=0.3,0.1

Type RM Length L Ch R = 1 ,9790.7  ,398.5,401.3,401.2
XS GIS Cut Line= 4
     1905567.096      613675.811     1905886.396      613418.224
     1905975.082      613304.717     1906188.771      612965.185
#Sta/Elev= 30
       0  921.48    58.6  928.52    97.7  927.08     127  923.44   244.2     900
   263.7  895.08   273.5  891.25     293   881.8   351.6  850.47   380.9  837.57
   400.5  830.33   419.8   824.7   429.4  823.18     496  820.09   506.3  819.55
   515.9  819.88   525.5  821.38   535.1  824.91   544.7  829.78   671.7   899.5
   759.8  952.35   779.4  964.86   828.3  998.62     838 1004.07   857.6 1012.43
     887 1026.68   896.8 1030.19   906.6 1031.04   935.9 1028.15   955.5 1030.82
#Mann= 3 , 0 , 0
       0     .07       0     496    .045       0   515.9      .1       0
Bank Sta=496,515.9
XS Rating Curve= 0 ,0
Exp/Cntr=0.3,0.1

Type RM Length L Ch R = 1 ,9389.3  ,368.3,367.9,368.5
XS GIS Cut Line= 3
     1905871.011       613972.45     1906194.997      613640.146
     1906484.323      613290.944
#Sta/Elev= 30
       0  977.81      58  980.12    67.7  979.25      87  973.65    96.7  969.71
     116  959.71   135.4  950.74   183.7  930.44   290.1   876.2   348.1  849.85
   396.4  829.94   415.8  822.81   425.4  820.27   454.4   816.4   464.1  815.96
   473.8  816.12     493  817.39   502.7  819.49   512.4  823.88   579.9  865.99
   724.6  950.16   743.9  963.19   811.5 1012.71   821.1 1018.64   830.8 1023.23
   840.4 1026.58     850 1028.18   869.4 1028.27   898.3 1032.52   917.6 1031.05
#Mann= 3 , 0 , 0
       0     .07       0   454.4    .045       0   473.8     .08       0
Bank Sta=454.4,473.8
XS Rating Curve= 0 ,0
Exp/Cntr=0.3,0.1

Type RM Length L Ch R = 1 ,9021.5  ,67.8,68.8,69
XS GIS Cut Line= 4
     1906173.631      614205.918     1906472.363      613862.947
     1906570.356      613761.656     1906897.391      613420.169
#Sta/Elev= 30
       0 1022.49    19.4 1013.12    58.1  990.53   145.2   948.5   222.6  909.58
   290.3  874.62   387.1  823.09   396.8  819.15   406.4  816.99     444  814.07
   454.8  813.94     459  814.09   520.6  815.63   558.2  819.01     577  824.69
   595.8  832.48   663.3  864.95     673  867.91   682.6  869.09   740.5  870.38
   788.8  868.06   827.4   863.7   875.6  856.38   914.2  847.32   923.8  846.61
   933.5  847.32   952.8  853.56   972.1  862.83  1020.3  880.75  1068.6  900.93
#Mann= 3 , 0 , 0
       0     .07       0     444    .045       0     459     .07       0
Bank Sta=444,459
XS Rating Curve= 0 ,0
Exp/Cntr=0.3,0.1

Type RM Length L Ch R = 1 ,8952.7  ,94.9,94,93.8
XS GIS Cut Line= 4
     1906210.089      614267.116     1906508.821      613924.145
     1906582.722      613847.757     1906921.263      613506.974
#Sta/Elev= 30
       0 1009.92    38.7 1009.25    48.4    1007    58.1 1003.49    96.8  987.41
   106.4  982.81   309.7   876.3   406.4  824.63   416.1     820   425.8  817.32
   454.8  813.92   464.7  813.37   474.2  813.28   483.8   813.5   532.1  816.34
   590.5   816.9   610.1  818.24   619.9  819.45   659.2  827.14   688.6  832.01
     718   838.7   737.6  840.86     816  840.79   874.8  838.83   884.6  839.36
   894.4  841.38   904.2  845.51   923.8  858.23   943.4  868.72  1041.5   911.2
#Mann= 3 , 0 , 0
       0     .07       0   464.7    .045       0   483.8     .06       0
Bank Sta=464.7,483.8
XS Rating Curve= 0 ,0
Exp/Cntr=0.3,0.1

Type RM Length L Ch R = 1 ,8858.7  ,85.1,85.2,84.9
XS GIS Cut Line= 4
     1906286.912      614321.803     1906585.644      613978.833
     1906646.575      613915.851     1907001.558      613559.058
#Sta/Elev= 30
       0  961.38    67.7  967.76   106.4  967.98   116.1  967.27   135.5  962.81
   193.5  945.75   212.9  938.05   241.9  924.01   309.7   885.9   338.7  868.26
   387.1  834.32   406.4  822.27   416.1  818.17   425.8  815.33   445.5  811.12
   454.8  810.86   464.6  811.12   532.7  813.41   590.9  816.98   639.2  821.48
   726.4  828.04   765.1  834.36   774.8  835.13   794.1  834.34   861.9  839.76
   871.5  842.18   881.2  846.38     978  905.14  1016.7  926.85  1045.8  941.53
#Mann= 3 , 0 , 0
       0     .07       0   445.5    .045       0   464.6     .06       0
Bank Sta=445.5,464.6
XS Rating Curve= 0 ,0
Exp/Cntr=0.3,0.1

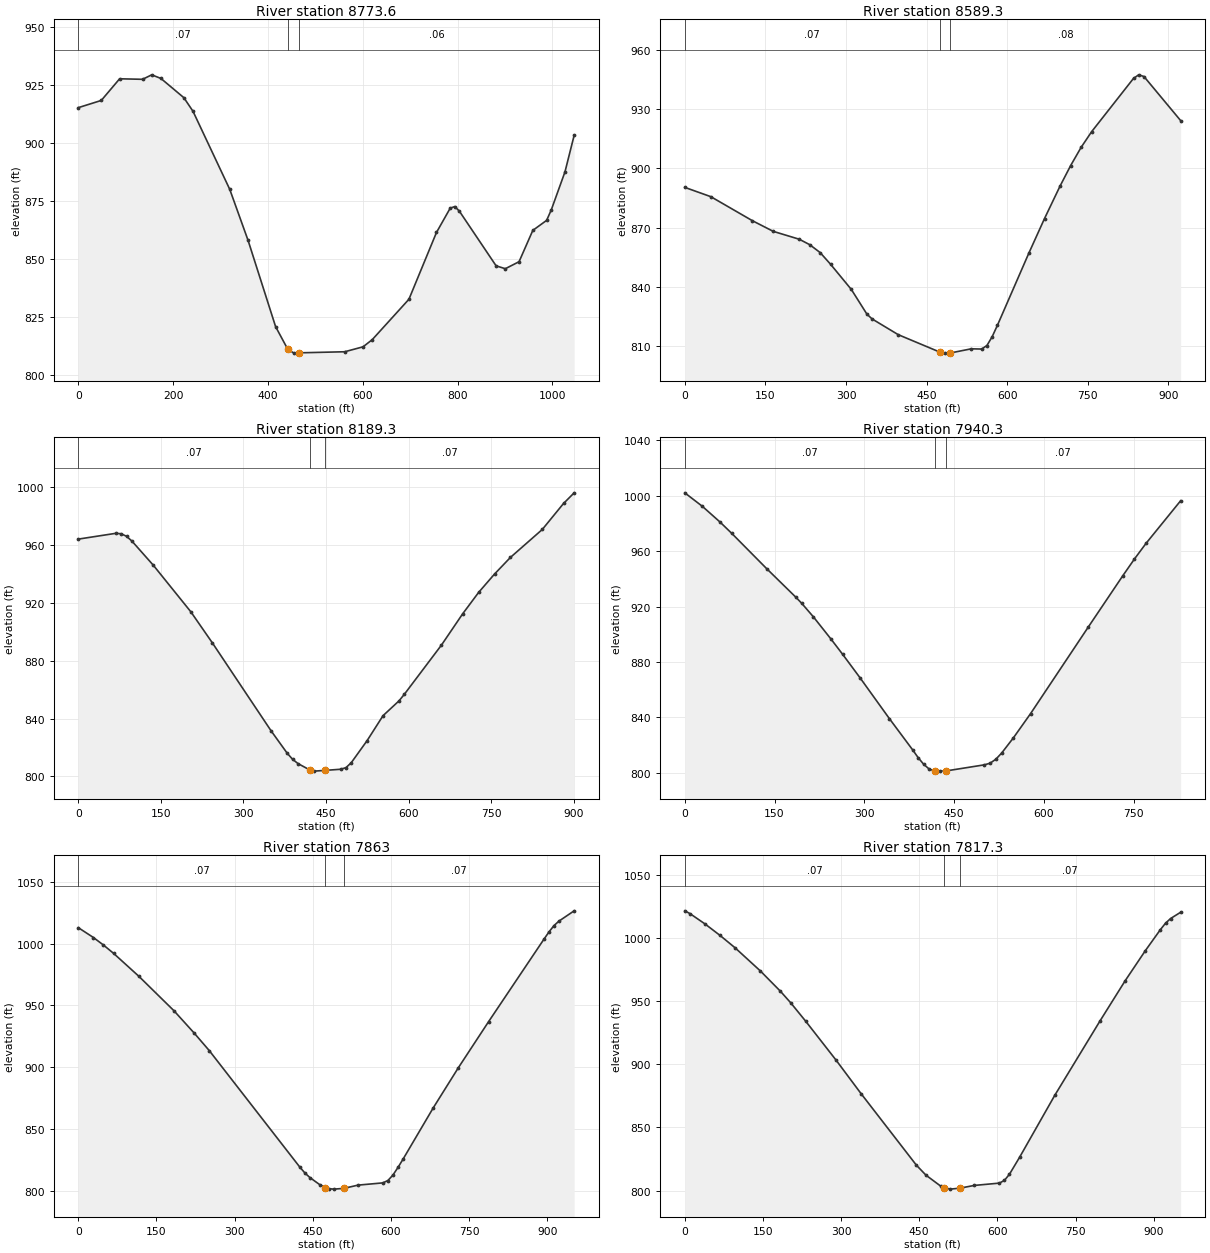
Type RM Length L Ch R = 1 ,8773.6  ,177.5,184.2,189.4
XS GIS Cut Line= 4
     1906338.995      614387.776     1906637.728      614044.805
     1906698.659      613981.823     1907053.641       613625.03
#Sta/Elev= 30
       0  915.37    48.4  918.47    87.1   927.8   135.5  927.58   154.8  929.51
   174.2  927.95   222.6  919.65   241.9  913.78   319.4  880.14   358.1  858.11
   416.1  820.98   441.8  811.21   454.8  809.57   464.6  809.69   561.8  810.16
   600.5  812.29   619.9  815.37   697.3  832.79   755.4  861.57   784.4  872.06
   794.1  872.74   803.8  870.72   881.2  847.19   900.6  845.95   929.6  848.97
   958.6  862.47   987.7  866.78   997.4  871.22  1026.4  887.67  1045.8  903.43
#Mann= 3 , 0 , 0
       0     .07       0   441.8    .045       0   464.6     .06       0
Bank Sta=441.8,464.6
XS Rating Curve= 0 ,0
Exp/Cntr=0.3,0.1

Type RM Length L Ch R = 1 ,8589.3  ,393.8,400,407
XS GIS Cut Line= 3
     1906366.527      614423.877     1906776.429      614165.877
     1907141.315      613922.773
#Sta/Elev= 30
       0  890.37    48.4  885.67   125.9  873.48   164.7  868.09   213.1   864.1
   232.5  861.35   251.9  857.35   271.2  851.46     310  838.65     339  826.14
   348.7  823.72   397.2  815.77   474.6  806.95   484.3  806.42   494.1  806.49
   533.1   808.6   552.5  808.49   562.3  810.28     572   814.7   581.8  820.49
   640.2  856.99   669.5   874.6   698.7   891.2   718.2  901.45   737.7  910.69
   757.2  918.59   835.1  945.57   844.8  947.38   854.6  946.52   922.8  924.21
#Mann= 3 , 0 , 0
       0     .07       0   474.6    .045       0   494.1     .08       0
Bank Sta=474.6,494.1
XS Rating Curve= 0 ,0
Exp/Cntr=0.3,0.1

Type RM Length L Ch R = 1 ,8189.3  ,249.9,249.1,247.4
XS GIS Cut Line= 3
     1906448.607      614658.884     1906857.802      614532.377
     1907310.895      614398.162
#Sta/Elev= 30
       0  964.15    68.1  968.15    77.9  967.84    87.6  966.09    97.3  962.81
   136.3  946.05   204.4  913.88   243.4  892.45   350.4  831.44   379.6  815.99
   389.4  811.82   399.1  808.89   420.8  804.42   428.3  803.66   447.6  804.15
   476.5  804.95   486.2  806.05   495.8  809.43   524.7  824.76   553.7  842.05
   582.6  852.24   592.2  856.74   659.8  890.85   698.3  912.46   727.3  927.27
   756.2  939.97   785.1  951.48     843  970.82   881.6   988.8   900.9  996.16
#Mann= 3 , 0 , 0
       0     .07       0   420.8    .045       0   447.6     .07       0
Bank Sta=420.8,447.6
XS Rating Curve= 0 ,0
Exp/Cntr=0.3,0.1

Type RM Length L Ch R = 1 ,7940.3  ,65.2,77.3,90.8
XS GIS Cut Line= 4
     1906562.105       614791.48     1906941.011      614752.417
     1907051.688      614706.844     1907340.751      614551.896
#Sta/Elev= 30
       0 1002.16    29.3  992.43    58.6  981.18    78.1  973.05   136.7  947.48
   185.6   926.8   195.3  922.45   214.9  912.63   244.2  896.67   263.7  885.64
     293  868.56   341.8  839.23   380.9  816.55   390.1  810.93   399.3  806.17
   408.5  802.74   417.9  801.38     427  801.27   436.2  801.39   500.6  805.81
   510.2  806.99   519.9   809.9   529.6  814.36   548.8   825.1   577.8  842.76
   674.2  905.23   732.1  942.39   751.4  954.38   770.7  965.63   828.6  996.44
#Mann= 3 , 0 , 0
       0     .07       0   417.9    .045       0   436.2     .07       0
Bank Sta=417.9,436.2
XS Rating Curve= 0 ,0
Exp/Cntr=0.3,0.1

Type RM Length L Ch R = 1 ,7863    ,45.2,45.7,45.2
XS GIS Cut Line= 4
     1906547.565      614816.436     1906991.575      614794.301
     1907102.252      614802.113       1907444.7      614602.894
#Sta/Elev= 30
       0 1012.88      29  1004.9    48.3   998.8    67.6  992.12     116   973.6
   183.6  945.62   222.3   927.6   251.3  913.39   425.2  819.03   434.9   814.3
   444.6  810.56     463  804.97   474.3  802.43   481.6  801.54   490.8  801.24
   509.3  801.84     537  804.49   584.5  806.29   594.2  808.22   603.8  812.59
   613.5  818.77   623.2  825.46   681.1  866.94   729.4   899.5   787.4  936.77
   893.7 1003.55   903.4 1009.46     913 1014.57   922.7 1018.25   951.7 1026.52
#Mann= 3 , 0 , 0
       0     .07       0   474.3    .045       0   509.3     .07       0
Bank Sta=474.3,509.3
XS Rating Curve= 0 ,0
Exp/Cntr=0.3,0.1

Type RM Length L Ch R = 1 ,7817.3  ,53.6,37.6,22.5
XS GIS Cut Line= 4
     1906551.905      614851.158     1906995.916      614829.023
     1907106.593      614836.835     1907449.041      614637.617
#Sta/Elev= 30
       0 1021.43     9.7 1019.29    38.7 1011.08    67.6 1001.98    96.6  992.14
     145  973.87   183.6  957.76     203  948.78     232   934.1   289.9  903.51
   338.2  876.83   444.6   820.1     463   812.2   490.8  803.68   497.6  802.42
   509.3  801.18   527.8  801.92   555.5   804.1   603.8  805.94   613.5   808.1
   623.2  812.99   642.5  826.31   710.1   875.4   797.1  934.38   845.4   966.2
     884  989.92     913 1006.62   922.7 1011.62   932.4 1015.33   951.7 1020.28
#Mann= 3 , 0 , 0
       0     .07       0   497.6    .045       0   527.8     .07       0
Bank Sta=497.6,527.8
XS Rating Curve= 0 ,0
Exp/Cntr=0.3,0.1

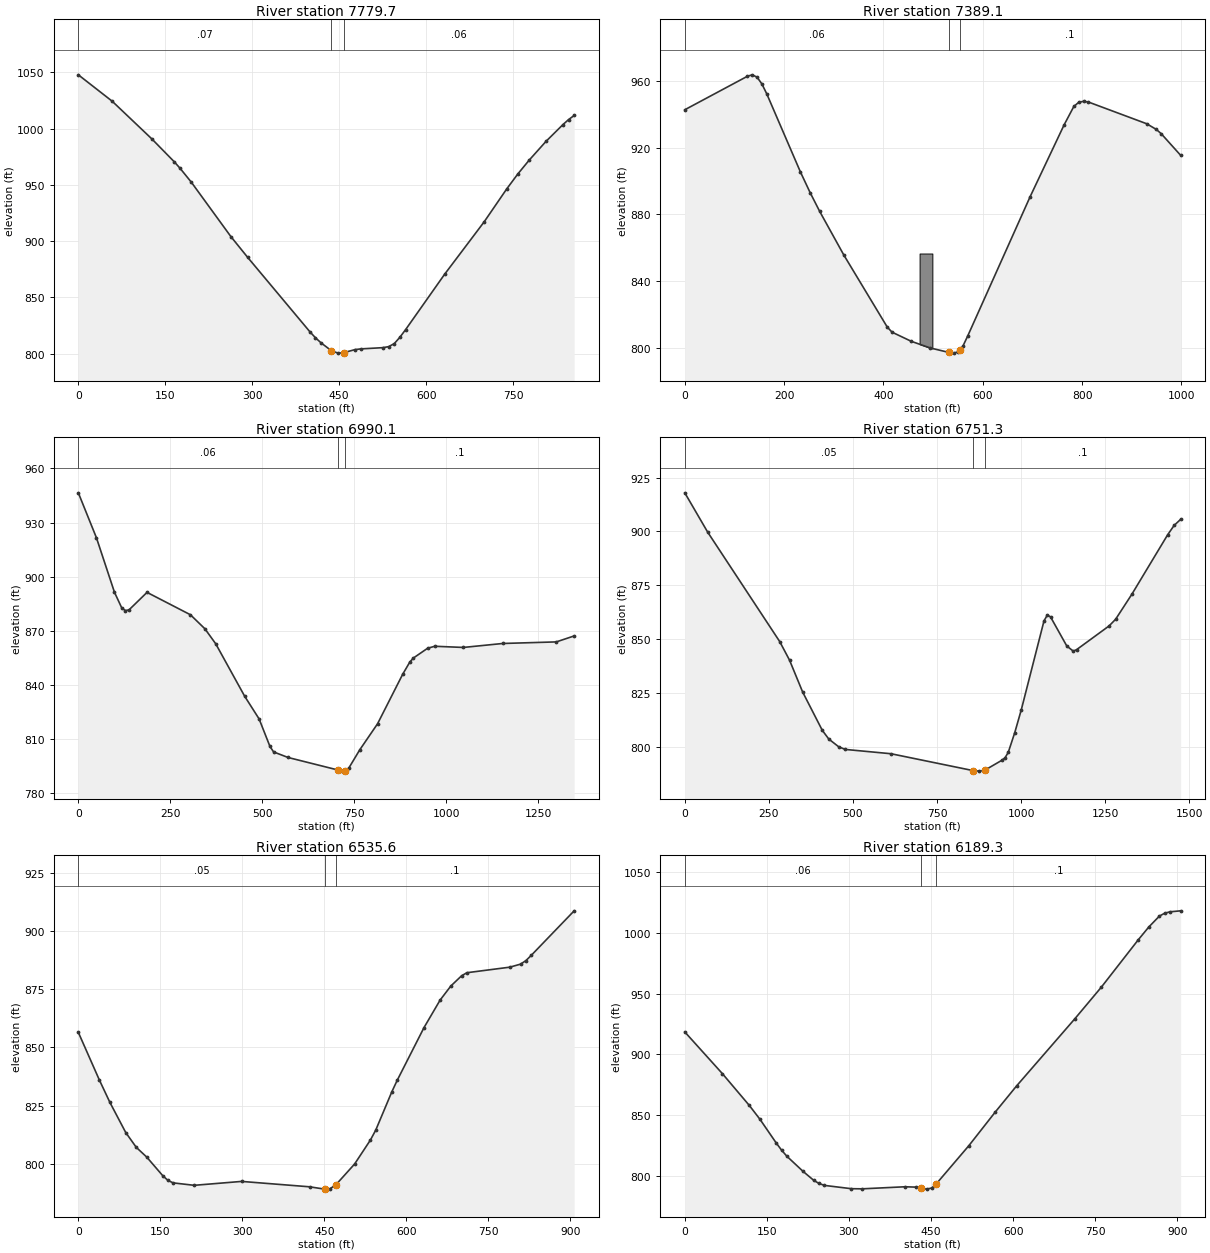
Type RM Length L Ch R = 1 ,7779.7  ,393.4,390.6,386.7
XS GIS Cut Line= 3
     1906692.313      615081.844     1907073.824      614865.698
     1907450.126      614686.011
#Sta/Elev= 30
       0 1047.83    58.5 1024.34   126.7  990.95   165.6  970.51   175.4  964.86
   194.9  952.46   263.1  904.16   292.3  885.54   399.5  819.52   409.2  814.14
     419  809.57   436.8  802.61   448.2  800.52   457.9  800.96   477.3  803.62
     487  804.27   525.8  805.39   535.5   806.3   545.2  809.02   554.9  814.68
   564.6  821.36   632.4   870.9   700.3  917.25   739.1  946.41   758.5  959.86
   777.9  972.02     807  988.74   836.1 1003.58   845.8 1008.03   855.5  1011.7
#Mann= 3 , 0 , 0
       0     .07       0   436.8    .045       0   457.9     .06       0
Bank Sta=436.8,457.9
XS Rating Curve= 0 ,0
Exp/Cntr=0.3,0.1

Type RM Length L Ch R = 1 ,7389.1  ,385.9,399,412
XS GIS Cut Line= 4
     1906872.435      615344.431     1907303.131      615167.027
     1907410.629      615090.525     1907738.316      614859.967
#Sta/Elev= 30
       0  942.62   126.2   962.7   135.9  963.54   145.6  962.12   155.3  958.04
     165  952.18   232.9  905.32   252.3  893.03   271.7   881.7   320.2  855.62
   407.6  812.49   417.3  809.41   456.1  803.93   494.1  799.96   531.8  797.28
   541.2  796.86   550.6  797.63   553.2  798.57     560  801.04   569.5  807.01
   695.5  890.64   763.9  933.64   783.4  944.61   793.2  947.08     803  947.67
   812.7  947.25     930  934.25   949.6  930.81   959.3  928.28   998.4  915.35
#Mann= 3 , 0 , 0
       0     .06       0   531.8    .045       0   553.2      .1       0
#Block Obstruct= 1 ,-1
  472.75  498.52  856.53
Bank Sta=531.8,553.2
XS Rating Curve= 0 ,0
Exp/Cntr=0.3,0.1

Type RM Length L Ch R = 1 ,6990.1  ,243.4,238.8,234
XS GIS Cut Line= 4
     1906783.459       615478.98     1907412.689      615488.506
     1907538.667       615483.32     1908131.115      615459.448
#Sta/Elev= 30
       0  946.48    49.2  921.61    98.3  891.39     118  882.77   127.8  881.26
   137.7  881.63   186.8  891.35   304.8  878.95   344.2  871.18   373.6  862.88
   452.3  833.83   491.6  821.25   521.1  806.01     531  802.98   570.3  799.91
   704.9  793.03   716.6  792.35   726.3  792.55     736  794.22   765.1   804.1
   813.7  818.58   881.8  845.91   901.2  852.69   910.9  854.96   949.8   860.4
   969.2   861.5    1047  860.85  1153.9  863.04  1299.7  863.92  1348.3  867.22
#Mann= 3 , 0 , 0
       0     .06       0   704.9    .045       0   726.3      .1       0
Bank Sta=704.9,726.3
XS Rating Curve= 0 ,0
Exp/Cntr=0.3,0.1

Type RM Length L Ch R = 1 ,6751.3  ,223.9,215.7,207.4
XS GIS Cut Line= 4
     1906879.813       616353.98      1907363.32      615743.736
     1907578.598      615689.917     1908041.271      615587.052
#Sta/Elev= 30
       0   917.9    68.1  899.65   282.2  848.92   311.4  840.31   350.4  825.53
   408.8  807.75   428.2   803.7   457.4  800.14   476.9  798.89   613.1  796.89
   855.8  789.11     875  788.82   891.3  789.18   942.6  793.83   952.2  794.99
   961.9  797.55   981.2  806.68  1000.5  817.21  1068.2  858.54  1077.9  861.18
  1087.5  860.37  1135.9  846.86  1155.2  844.48  1164.9  845.14  1261.6  856.16
    1281  859.24  1329.4  870.86  1435.8  898.43  1455.1  902.79  1474.4  905.59
#Mann= 3 , 0 , 0
       0     .05       0   855.8    .045       0   891.3      .1       0
Bank Sta=855.8,891.3
XS Rating Curve= 0 ,0
Exp/Cntr=0.3,0.1

Type RM Length L Ch R = 1 ,6535.6  ,343.3,346.3,348.8
XS GIS Cut Line= 4
     1907301.879      616174.492      1907582.07      615882.625
     1907672.208      615819.815     1908029.987      615658.667
#Sta/Elev= 30
       0  856.49    38.5  835.97    57.8  826.32    86.7  813.38     106     807
   125.2  802.79   154.1  794.88   163.8  792.79   173.4  791.71   211.9  790.66
   298.6  792.34   422.9  790.02   450.4  789.02   459.5  789.09   470.4  790.72
   505.3  799.84   534.1  810.12   543.9  814.41   573.3  830.88   583.1  835.82
   632.2  858.55   661.6  870.37   681.2  876.42   700.8  880.82   710.6  882.16
   789.1  884.55   808.8  885.86   818.6  887.38   828.4  889.65   906.8   908.8
#Mann= 3 , 0 , 0
       0     .05       0   450.4    .045       0   470.4      .1       0
Bank Sta=450.4,470.4
XS Rating Curve= 0 ,0
Exp/Cntr=0.3,0.1

Type RM Length L Ch R = 1 ,6189.3  ,397.6,400.2,402.5
XS GIS Cut Line= 3
     1907412.799      616348.337     1907812.543      616138.497
      1908212.71      615923.035
#Sta/Elev= 30
       0  918.58    68.7  884.22   117.8  858.09   137.4  846.61   166.8   827.3
   176.7   821.3   186.5   816.2   215.9  803.82   235.6  796.35   245.4  793.76
   255.2  792.19   304.2  789.48   323.9  789.36   402.4  791.06     422  790.78
   431.8   789.9   441.7  789.12   451.5  790.06     459  793.19   519.2     825
   567.5  852.73   606.2  874.08   712.6  929.36   760.9  955.33   828.6  994.46
   847.9 1005.03   867.3 1014.02     877 1016.37   886.6 1017.51     906 1018.32
#Mann= 3 , 0 , 0
       0     .06       0   431.8    .045       0     459      .1       0
Bank Sta=431.8,459
XS Rating Curve= 0 ,0
Exp/Cntr=0.3,0.1

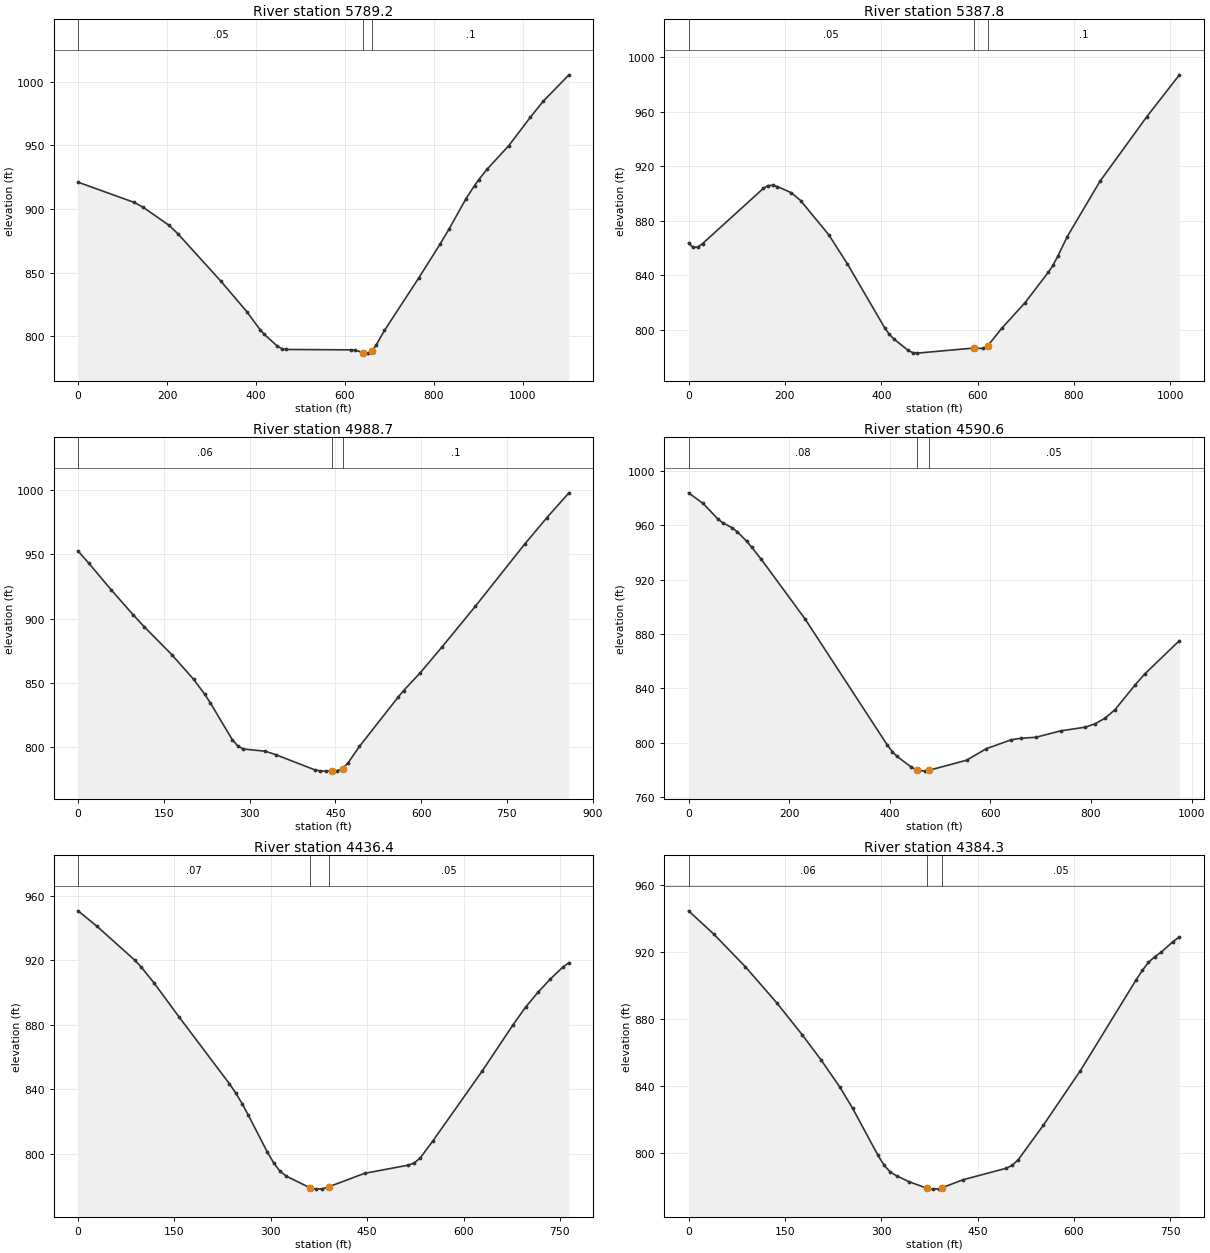
Type RM Length L Ch R = 1 ,5789.2  ,406.4,401.3,395.4
XS GIS Cut Line= 4
     1907382.417      616734.188     1907925.623      616519.483
     1908032.157      616477.677     1908417.264      616351.833
#Sta/Elev= 30
       0  921.07   126.6  905.13     146  901.43   204.4  887.21   223.9  880.71
   321.2  843.25   379.7  819.22   408.9   805.3   418.6  801.57   447.8  792.31
   457.5  790.31   467.3  789.62   612.7  789.31   622.2  789.06   641.3  787.19
   650.9  786.74   660.4   788.1   669.9  792.87     689  804.58   766.1  845.85
   814.3  872.62   833.6  883.95   872.2  908.07   891.5  918.45   901.1  923.15
   920.4  931.56   968.6  949.85  1016.9  972.07  1045.8  984.64  1103.7 1005.44
#Mann= 3 , 0 , 0
       0     .05       0   641.3    .045       0   660.4      .1       0
Bank Sta=641.3,660.4
XS Rating Curve= 0 ,0
Exp/Cntr=0.3,0.1

Type RM Length L Ch R = 1 ,5387.8  ,401.4,399.1,396
XS GIS Cut Line= 4
     1907673.216      617194.257     1908082.239       616899.76
      1908200.56      616814.483     1908506.115      616607.886
#Sta/Elev= 30
       0  863.68     9.7  860.44    19.4  860.85    29.1  863.29   155.1   903.7
   164.8  905.76   174.5  906.07   184.2   905.1   213.2   900.6   232.6  894.81
   290.8  869.82   329.6  848.45   407.1  801.48   416.8  796.73   426.5  793.23
   455.6  785.05   465.2  783.38   474.9  782.99   591.5   786.7     611   786.4
   620.7  788.24   649.9  801.16   698.4  820.01   746.9  842.41   756.6  847.56
   766.3  854.02   785.8  868.32   853.7   908.9   950.8  956.21  1018.7     987
#Mann= 3 , 0 , 0
       0     .05       0   591.5    .045       0   620.7      .1       0
Bank Sta=591.5,620.7
XS Rating Curve= 0 ,0
Exp/Cntr=0.3,0.1

Type RM Length L Ch R = 1 ,4988.7  ,393.2,398.2,402.3
XS GIS Cut Line= 4
     1908123.923      617418.916      1908421.48       617131.15
      1908485.87      617071.356     1908748.737      616830.368
#Sta/Elev= 30
       0  952.62    19.2  942.93    57.8  922.45    96.3  902.93   115.5  893.69
   163.6  871.99   202.2  852.59   221.4  841.05     231   834.5   269.6  805.66
   279.2  800.74   288.8  798.32   327.3  796.63   346.6  793.77   413.9  782.11
   423.7  781.21   433.5  781.09   443.2   781.2     453  781.36   462.8  783.06
   472.5  787.72     492  800.34   559.6   838.7   569.3  843.89   598.2  857.65
   636.8  878.05   694.6   909.5   781.3  958.17   819.9  978.69   858.4     998
#Mann= 3 , 0 , 0
       0     .06       0   443.2    .045       0   462.8      .1       0
Bank Sta=443.2,462.8
XS Rating Curve= 0 ,0
Exp/Cntr=0.3,0.1

Type RM Length L Ch R = 1 ,4590.6  ,147.4,154.1,159.5
XS GIS Cut Line= 4
     1908274.377      617606.066     1908656.723      617422.382
     1908742.347      617372.958     1909142.834      617161.966
#Sta/Elev= 30
       0  983.93    28.9  976.08    57.8  964.88    67.5  962.01    86.8  958.16
    96.4   955.4   115.7  948.19   125.3  943.97   144.6  934.95   231.4  891.16
   395.3   798.1   404.9  793.42   414.5   789.8   442.2  782.16   454.1  779.69
   469.1  779.01   478.1  779.64   552.6  787.05   591.9  795.54   641.1  802.06
   660.8  803.24   690.3  803.92   739.5  808.64   788.7   811.4   808.4  813.93
   828.1  818.06   847.8  824.31   887.2  842.33   906.8  850.55   975.7  875.11
#Mann= 3 , 0 , 0
       0     .08       0   454.1    .045       0   478.1     .05       0
Bank Sta=454.1,478.1
XS Rating Curve= 0 ,0
Exp/Cntr=0.3,0.1

Type RM Length L Ch R = 1 ,4436.4  ,54.7,52.1,50.7
XS GIS Cut Line= 4
     1908418.876      617641.132     1908734.848      617533.493
     1908821.653      617500.507     1909137.626      617382.452
#Sta/Elev= 30
       0  950.72    29.4  941.14    88.4  920.09    98.2  915.89   117.8  906.25
   157.1  884.99   235.6  843.53   245.4   837.8   255.3  831.27   265.1  823.98
   294.5  801.27   304.4  794.54   314.2  789.34     324  786.31   361.7  778.91
     371  778.24   380.2  778.46   391.3  779.86   445.9  788.02   513.4  793.07
     523   794.4   532.7  797.67     552     808     629  851.41   677.2   880.2
   696.5     891   715.8   900.2   735.1  908.47   754.3  915.75     764   918.6
#Mann= 3 , 0 , 0
       0     .07       0   361.7    .045       0   391.3     .05       0
Bank Sta=361.7,391.3
XS Rating Curve= 0 ,0
Exp/Cntr=0.3,0.1

Type RM Length L Ch R = 1 ,4384.3  ,58.6,58.5,58.3
XS GIS Cut Line= 4
     1908446.653      617682.799     1908762.626       617575.16
     1908849.431      617542.174     1909165.403      617424.118
#Sta/Elev= 30
       0  944.55    39.3   930.6    88.4  911.12   137.4   889.5   176.7  870.54
   206.2  855.44   235.6  839.09   255.3  826.53   294.5   798.6   304.4   792.4
   314.2  788.33     324  786.08   343.1  782.63     371   778.7     380  778.17
   389.5  778.34     395  779.04   426.7  783.72   494.1  790.62   503.8  792.35
   513.4  795.88     552  816.27   609.8  848.97   696.5   903.2   706.2   908.9
   715.8  913.72   725.4  917.06   735.1  919.69   754.3  926.21     764  928.95
#Mann= 3 , 0 , 0
       0     .06       0     371    .045       0     395     .05       0
Bank Sta=371,395
XS Rating Curve= 0 ,0
Exp/Cntr=0.3,0.1

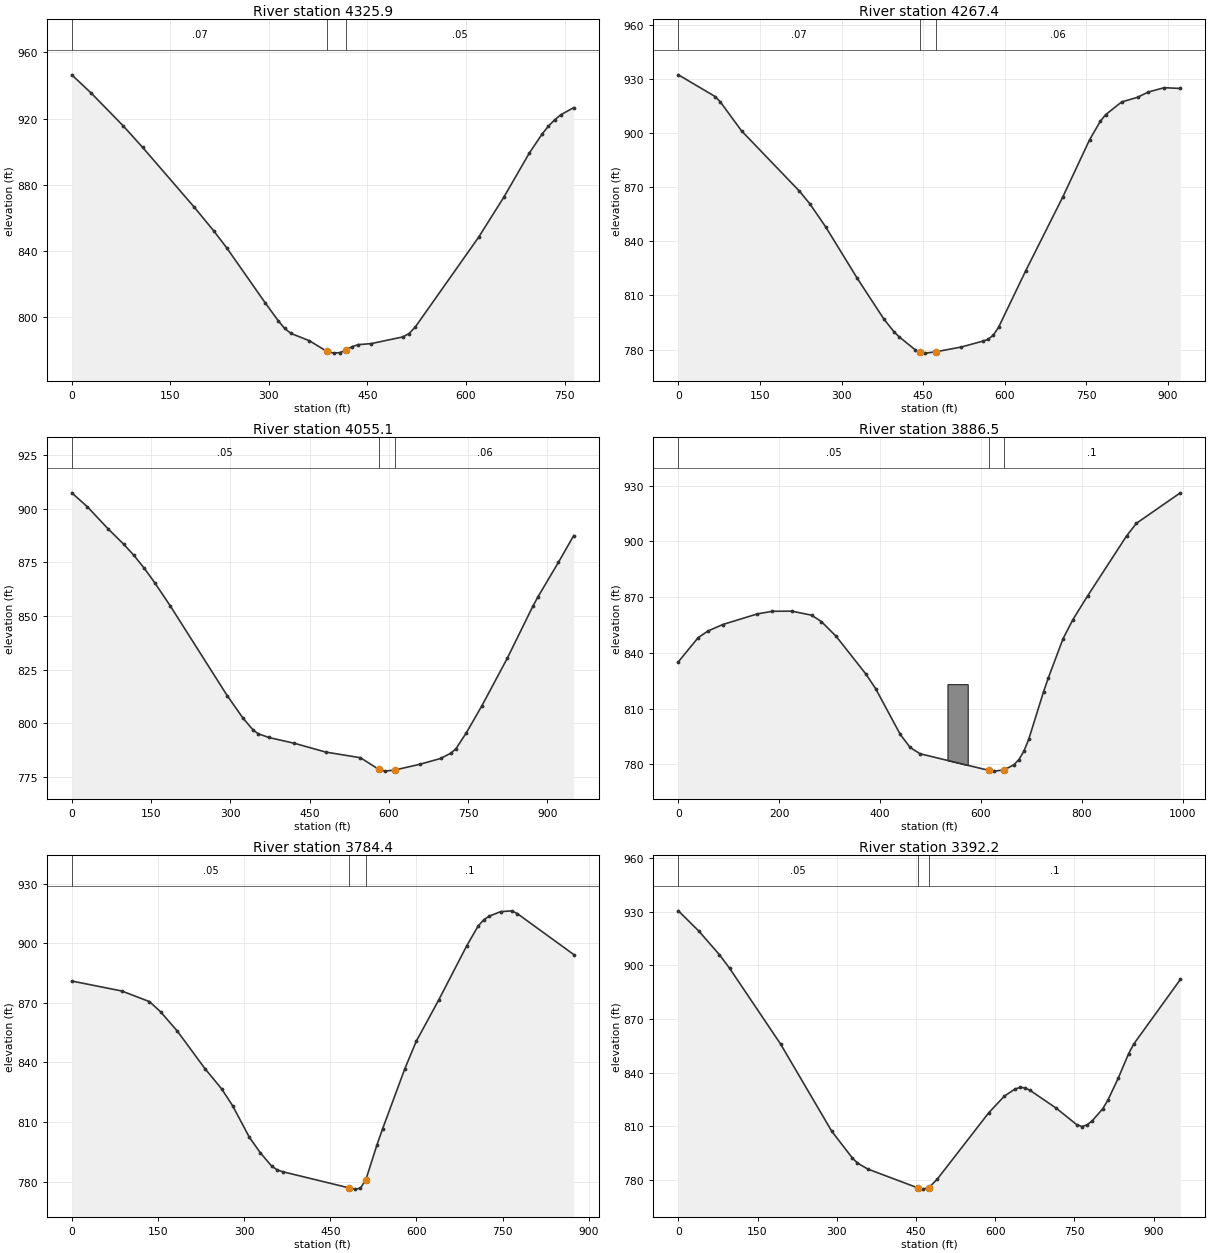
Type RM Length L Ch R = 1 ,4325.9  ,58.7,58.4,58.2
XS GIS Cut Line= 4
     1908453.598      617741.827      1908769.57      617634.188
     1908856.376      617601.202     1909172.348      617483.146
#Sta/Elev= 30
       0  946.41    29.4  935.46    78.5  915.49     108   902.5   186.5   866.4
     216  852.16   235.6  841.99   294.5  808.58   314.2  797.82     324  793.14
   333.8   790.1   361.7  785.69   388.5   779.2   398.8  778.21   408.1  778.53
   417.4  780.04   426.7  782.14   436.3  783.35   455.6  783.95   503.8  787.99
   513.4  790.06     523  794.07   619.4  848.35     658  872.71   696.5  899.17
   715.8  910.56   725.4  915.36   735.1  919.26   744.7  922.35     764  926.58
#Mann= 3 , 0 , 0
       0     .07       0   388.5    .045       0   417.4     .05       0
Bank Sta=388.5,417.4
XS Rating Curve= 0 ,0
Exp/Cntr=0.3,0.1

Type RM Length L Ch R = 1 ,4267.4  ,208.3,212.4,218.4
XS GIS Cut Line= 4
     1908425.321      617851.273     1908814.709      617679.327
     1908892.499      617645.568      1909270.46      617481.545
#Sta/Elev= 30
       0  932.16    67.7  920.12    77.4  917.07   116.1  901.14   222.5  867.77
   241.8  860.68   270.9   847.9   328.9  819.44   377.3  797.12   396.6  789.77
   406.3  786.98   435.1  779.97   444.5  778.46   453.9  778.08   472.8   778.8
   520.3  781.48   559.5  784.73   569.3  785.74   579.1   788.1   588.9  792.66
     638  823.46   706.7  864.67   755.7  896.18   775.3  906.36   785.1  910.05
   814.6  917.13     844  919.73   863.6  922.64     893  925.04   922.5  924.61
#Mann= 3 , 0 , 0
       0     .07       0   444.5    .045       0   472.8     .06       0
Bank Sta=444.5,472.8
XS Rating Curve= 0 ,0
Exp/Cntr=0.3,0.1

Type RM Length L Ch R = 1 ,4055.1  ,172.6,168.6,163
XS GIS Cut Line= 4
      1908354.64      617944.952     1908840.751      617882.452
      1908988.32      617821.688     1909264.362      617703.632
#Sta/Elev= 30
       0  907.41    29.4  900.95    68.6  890.67      98  883.53   117.6  878.27
   137.2  872.25   156.8  865.57   186.2  854.79   294.1  812.88   323.5  802.56
   343.1  796.84   352.9   795.1   372.5  793.37   421.5  790.63   480.3  786.56
   546.4  783.91   580.5  778.55   593.4  777.66   612.2  778.22   659.4   780.9
   698.1  783.57   717.5  786.06   727.2  788.16   746.6  795.49   775.6  807.89
     824   830.2   872.4  854.44   882.1  858.86   920.9  874.98   949.9  887.48
#Mann= 3 , 0 , 0
       0     .05       0   580.5    .045       0   612.2     .06       0
Bank Sta=580.5,612.2
XS Rating Curve= 0 ,0
Exp/Cntr=0.3,0.1

Type RM Length L Ch R = 1 ,3886.5  ,102,102.1,101.2
XS GIS Cut Line= 4
      1908519.57      618224.466     1908981.506      617968.845
     1909156.853      617881.171     1909396.306       617753.98
#Sta/Elev= 30
       0  835.15    39.1  848.11    58.7  851.72      88  855.22   156.4  860.91
   185.8  862.34   224.9   862.4     264  860.25   283.5  856.81   312.9  848.84
   371.5  828.65   391.1   820.7     440  796.03   459.5  789.04   479.1  785.65
   616.2  776.66     626   776.3   645.6  776.96   665.2  779.71     675   782.5
   684.8  786.92   694.6  793.46     724  819.06   733.7  826.69   762.7  847.62
   782.1  857.85   811.1  870.53   888.6  902.91     908   909.7   995.1   926.1
#Mann= 3 , 0 , 0
       0     .05       0   616.2    .045       0   645.6      .1       0
#Block Obstruct= 1 ,-1
  533.44  573.58  823.09
Bank Sta=616.2,645.6
XS Rating Curve= 0 ,0
Exp/Cntr=0.3,0.1

Type RM Length L Ch R = 1 ,3784.4  ,392.9,392.2,390.6
XS GIS Cut Line= 4
     1908692.601      618247.771     1909094.328      618016.316
     1909191.445       617972.73      1909479.64      617877.243
#Sta/Elev= 30
       0  880.94    86.9  875.94   135.2  870.59   154.5  865.48   183.5  855.84
   231.8  836.86   260.8   826.7   280.1  818.12   309.1  802.31   328.4  794.42
   347.7  787.86   357.4  785.91     367  784.96     483   776.8   492.7  776.19
   502.3  776.61     512  781.03   531.4  798.61     541  806.51   579.9  836.91
   599.5  850.55   638.6  871.34   687.6  898.73   707.2  908.56     717  911.75
   726.8  913.62   746.4  915.85     766  916.28   775.8  914.84   873.7  894.28
#Mann= 3 , 0 , 0
       0     .05       0     483    .045       0     512      .1       0
Bank Sta=483,512
XS Rating Curve= 0 ,0
Exp/Cntr=0.3,0.1

Type RM Length L Ch R = 1 ,3392.2  ,452.5,446.2,439.9
XS GIS Cut Line= 4
     1908783.459       618566.48     1909146.306      618405.021
     1909246.192      618353.904     1909624.777      618126.819
#Sta/Elev= 30
       0  930.53    38.8  919.21    77.5   906.1    96.9  898.48   193.7  856.02
   290.6  807.27   329.3  792.48     339   789.6   358.4  786.22   453.2  775.69
   462.6  774.95   474.5  775.76   490.6  780.61   587.8  817.59   617.3  826.89
   636.9  830.76   646.7  831.79   656.5  831.58   666.3  830.16   715.4  820.28
   754.6  810.99   764.4  809.95   774.2  810.88     784  813.19   803.7  819.81
   813.5  824.67   833.1  836.89   852.7  850.58   862.5  856.04   950.8  892.14
#Mann= 3 , 0 , 0
       0     .05       0   453.2    .045       0   474.5      .1       0
Bank Sta=453.2,474.5
XS Rating Curve= 0 ,0
Exp/Cntr=0.3,0.1

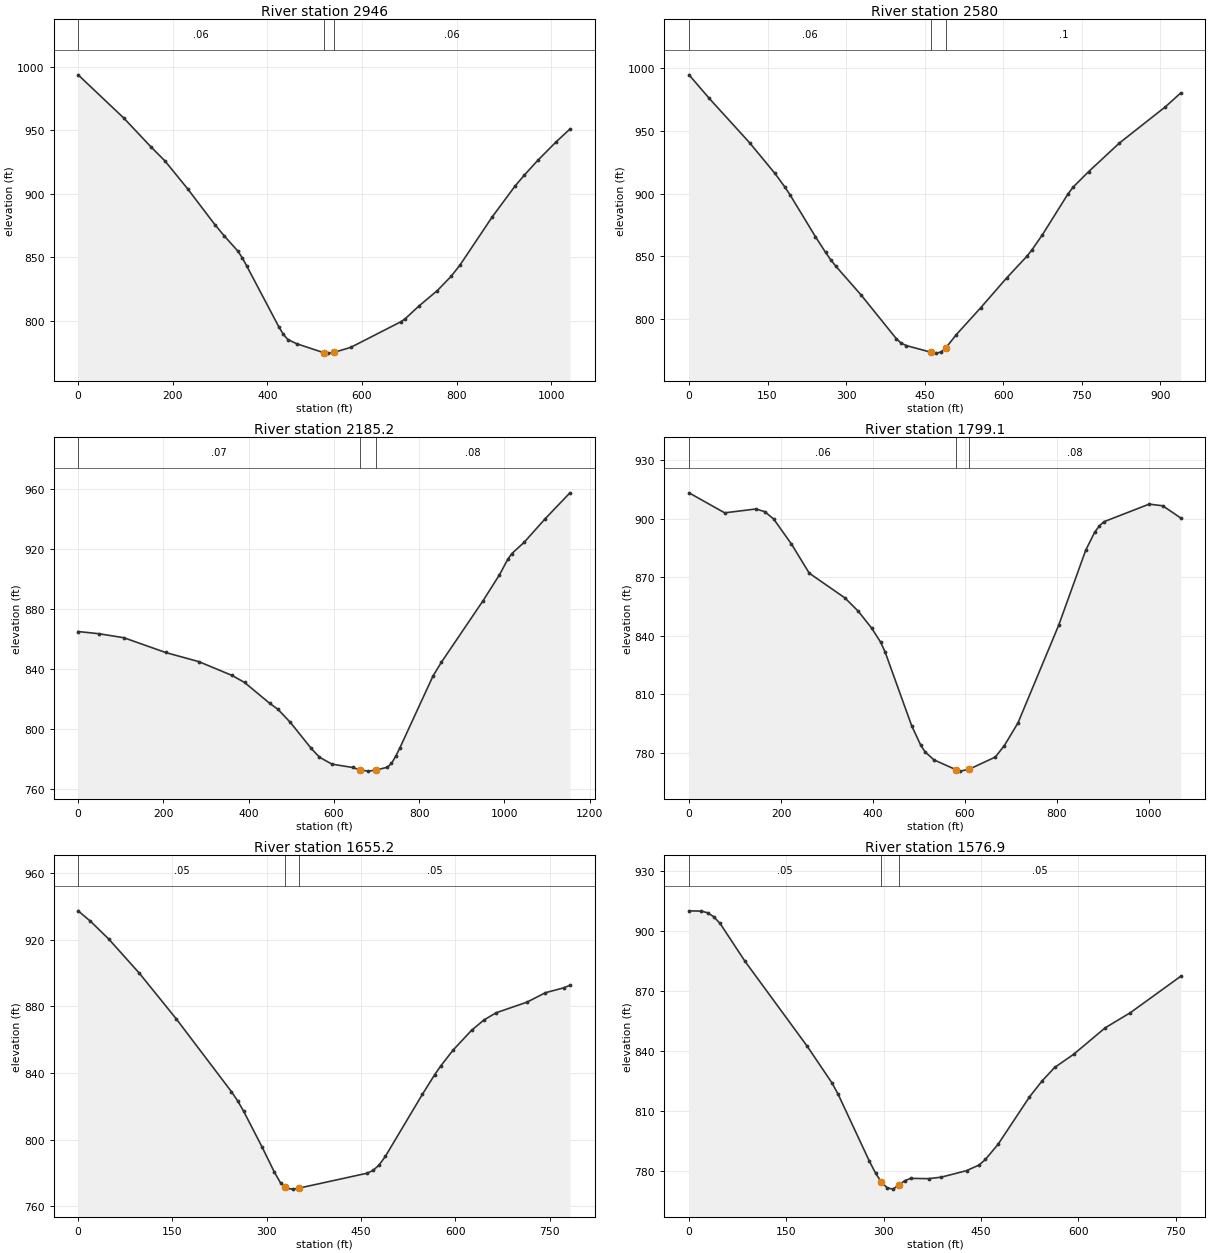
Type RM Length L Ch R = 1 ,2946    ,353.3,366,378.5
XS GIS Cut Line= 4
     1909139.375       618988.84     1909444.917      618667.174
     1909569.917      618550.855     1909918.876      618307.799
#Sta/Elev= 30
       0  993.45    96.4  959.47   154.3   936.6   183.2  925.83   231.5  903.75
   289.3  875.44   308.6  866.82   337.6  854.76   347.2  849.29   356.8  842.75
   424.4  795.02     434  789.11   443.6     785   462.6  781.71   519.5  774.72
     529   774.4   540.1   774.9   576.4  778.95     682  799.04   691.7  801.54
   720.7  811.56   759.4  823.65   788.4   834.8   807.7  843.95   875.4  881.64
   923.7  905.93     943  914.39     972  926.24  1010.7  940.75  1039.7  950.78
#Mann= 3 , 0 , 0
       0     .06       0   519.5    .045       0   540.1     .06       0
Bank Sta=519.5,540.1
XS Rating Curve= 0 ,0
Exp/Cntr=0.3,0.1

Type RM Length L Ch R = 1 ,2580    ,403.3,394.8,386.9
XS GIS Cut Line= 4
     1909193.624      619072.157     1909596.618      618909.504
     1909698.064      618889.939     1910098.853      618868.459
#Sta/Elev= 30
       0  994.73    38.6  975.99   115.9  940.53   164.2  916.14   183.5  905.06
   193.2  898.92   241.4  865.83   260.8  853.26   270.4   847.5   280.1   842.4
   328.4  819.44     396  784.48   405.6  780.85   415.3  778.99   462.8  773.62
   472.2     773   481.5  773.91   490.7  777.24   509.7  787.36   557.5  809.35
   606.4  832.79   645.6  850.33   655.4  855.54     675  867.34   723.9  899.91
   733.7  905.33     763  917.53   821.8  940.31   909.9  969.29   939.3  980.35
#Mann= 3 , 0 , 0
       0     .06       0   462.8    .045       0   490.7      .1       0
Bank Sta=462.8,490.7
XS Rating Curve= 0 ,0
Exp/Cntr=0.3,0.1

Type RM Length L Ch R = 1 ,2185.2  ,383.2,386.2,388.4
XS GIS Cut Line= 4
     1909070.026      619510.164     1909676.363      619292.282
     1909736.963      619254.674     1910131.264      619063.766
#Sta/Elev= 30
       0  864.72    48.8  863.25   107.4  860.58     205  850.76   283.1  844.66
   361.2  835.44   390.5  830.76     449  816.98   468.6  812.92   497.9  804.17
   546.7  786.87   566.2  780.97   595.5  776.36   644.3  774.13   662.1  772.47
     680  771.71   697.8  772.34   725.4  774.32   735.1  776.88   744.8  781.48
   754.6  787.11   832.4  835.05   851.9  844.15   949.3  885.01   988.2   902.4
  1007.7  912.73  1017.4  916.65  1046.6  924.24  1095.3  939.76  1153.7  957.12
#Mann= 3 , 0 , 0
       0     .07       0   662.1    .045       0   697.8     .08       0
Bank Sta=662.1,697.8
XS Rating Curve= 0 ,0
Exp/Cntr=0.3,0.1

Type RM Length L Ch R = 1 ,1799.1  ,157,143.8,130.4
XS GIS Cut Line= 4
     1909323.932      619809.644     1909836.085      619631.692
     1909921.706      619592.453     1910269.253      619334.404
#Sta/Elev= 30
       0  913.19    77.5  902.94   145.2   904.9   164.6  903.56     184  899.78
   222.7  886.94   261.4  872.01   338.9  859.34   367.9  852.53     397  843.87
   416.3  836.76     426  831.82   484.1  793.79   503.5  783.98   513.1  780.44
   532.5  776.34   579.9  771.34   589.3  770.56   608.1  771.43   665.9  777.78
   685.6  783.69   715.1  795.25   803.6   845.3   862.6  883.88   882.3  893.16
   892.2  896.27     902  898.38  1000.4   907.4  1029.9  906.55  1069.2  900.27
#Mann= 3 , 0 , 0
       0     .06       0   579.9    .045       0   608.1     .08       0
Bank Sta=579.9,608.1
XS Rating Curve= 0 ,0
Exp/Cntr=0.3,0.1

Type RM Length L Ch R = 1 ,1655.2  ,76.9,78.4,79.7
XS GIS Cut Line= 4
     1909723.346      619962.855      1909942.53      619754.522
     1910009.804      619646.015     1910242.009      619381.258
#Sta/Elev= 30
       0  937.26    19.5  931.05    48.8  920.29    97.6  899.71   156.1   872.4
   243.9  828.69   253.6  823.27   263.4  816.86   292.6  795.46   312.2  780.36
     322  773.93   329.8  771.35   331.9  770.66   341.7  770.22   351.5  770.85
   459.4  779.76   469.2  781.46     479  784.84   488.8  789.98   547.4  827.05
     567  838.87   576.8   844.2   596.4  853.69   625.7  865.54   645.3   871.7
   664.8  876.07   713.8  882.44   743.1   888.1   772.4  891.06   782.2   892.6
#Mann= 3 , 0 , 0
       0     .05       0   329.8    .045       0   351.5     .05       0
Bank Sta=329.8,351.5
XS Rating Curve= 0 ,0
Exp/Cntr=0.3,0.1

Type RM Length L Ch R = 1 ,1576.9  ,65.4,65.5,65.6
XS GIS Cut Line= 4
     1909859.956      620022.751     1910016.206      619781.432
     1910057.873      619722.404     1910267.943      619383.862
#Sta/Elev= 30
       0  910.24    19.2  910.08    28.8  909.25    38.3  907.22    47.9  903.91
    86.2  884.99   182.1  842.39   220.4  823.96     230  818.19   277.9  784.81
   287.5  778.76   296.5  774.19   305.6  771.32   314.6  770.69   323.6  772.83
   332.6  774.92   341.7   776.1   369.5  775.94   388.9  776.69   427.8  779.95
   447.2  782.79   456.9  785.57   476.4  793.15   524.9  816.94   544.4  824.99
   563.8  831.73     593  838.31   641.6  851.58   680.4  859.17   758.2  877.46
#Mann= 3 , 0 , 0
       0     .05       0   296.5    .045       0   323.6     .05       0
Bank Sta=296.5,323.6
XS Rating Curve= 0 ,0
Exp/Cntr=0.3,0.1