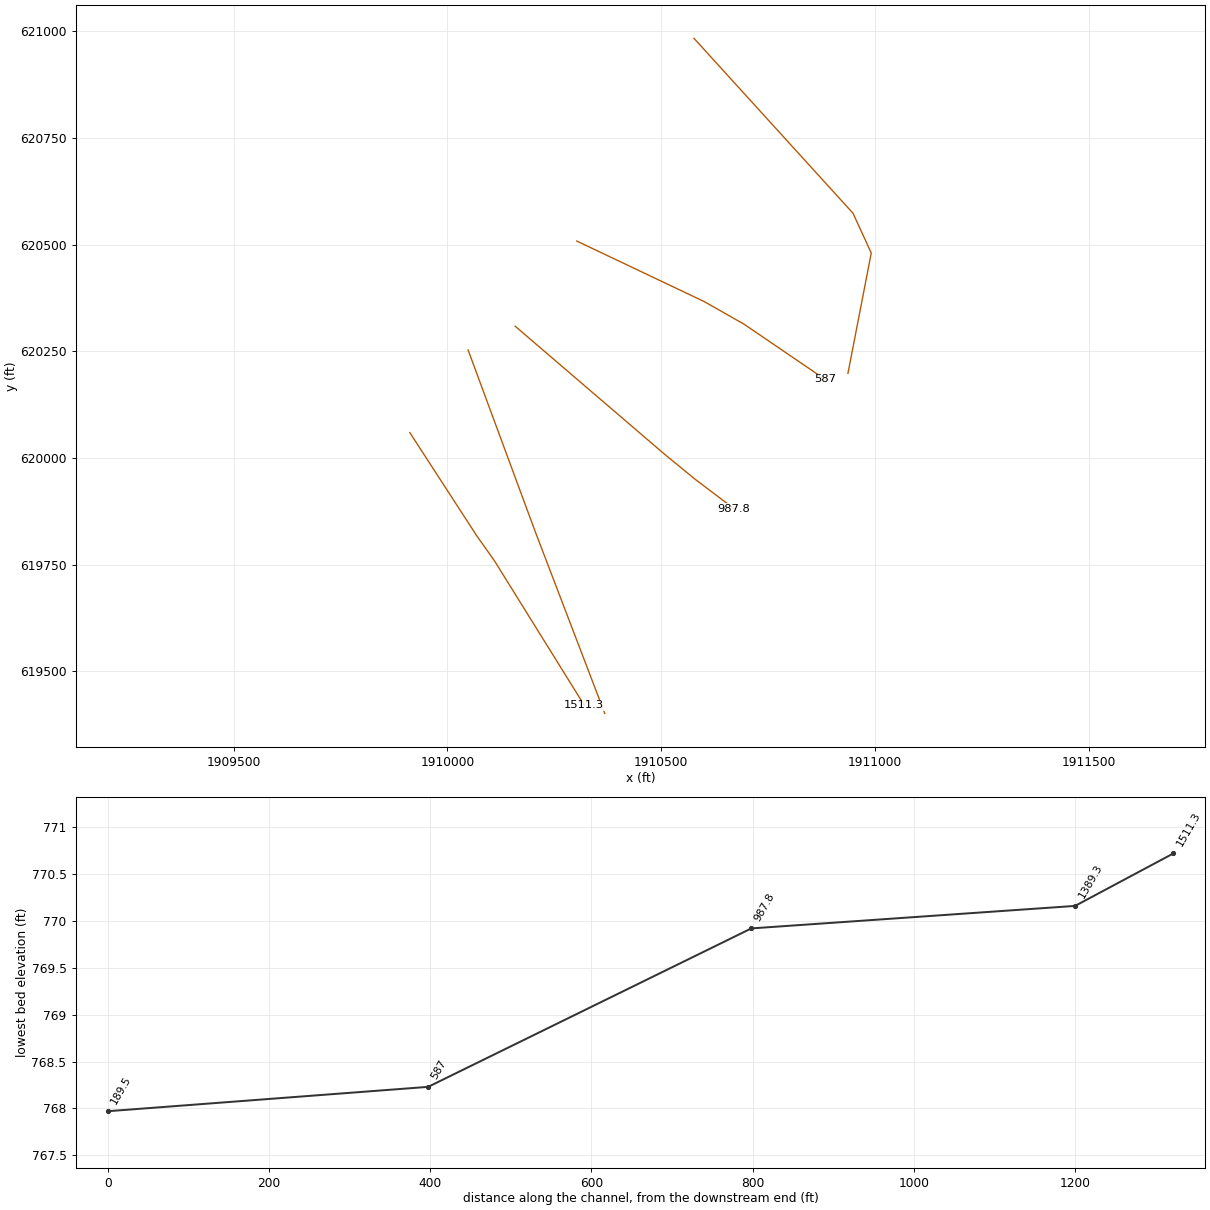
HEC-RAS study CanoeRun.prj: CanoeRun

--- CanoeRun.g01 (geometry) --- (continued)

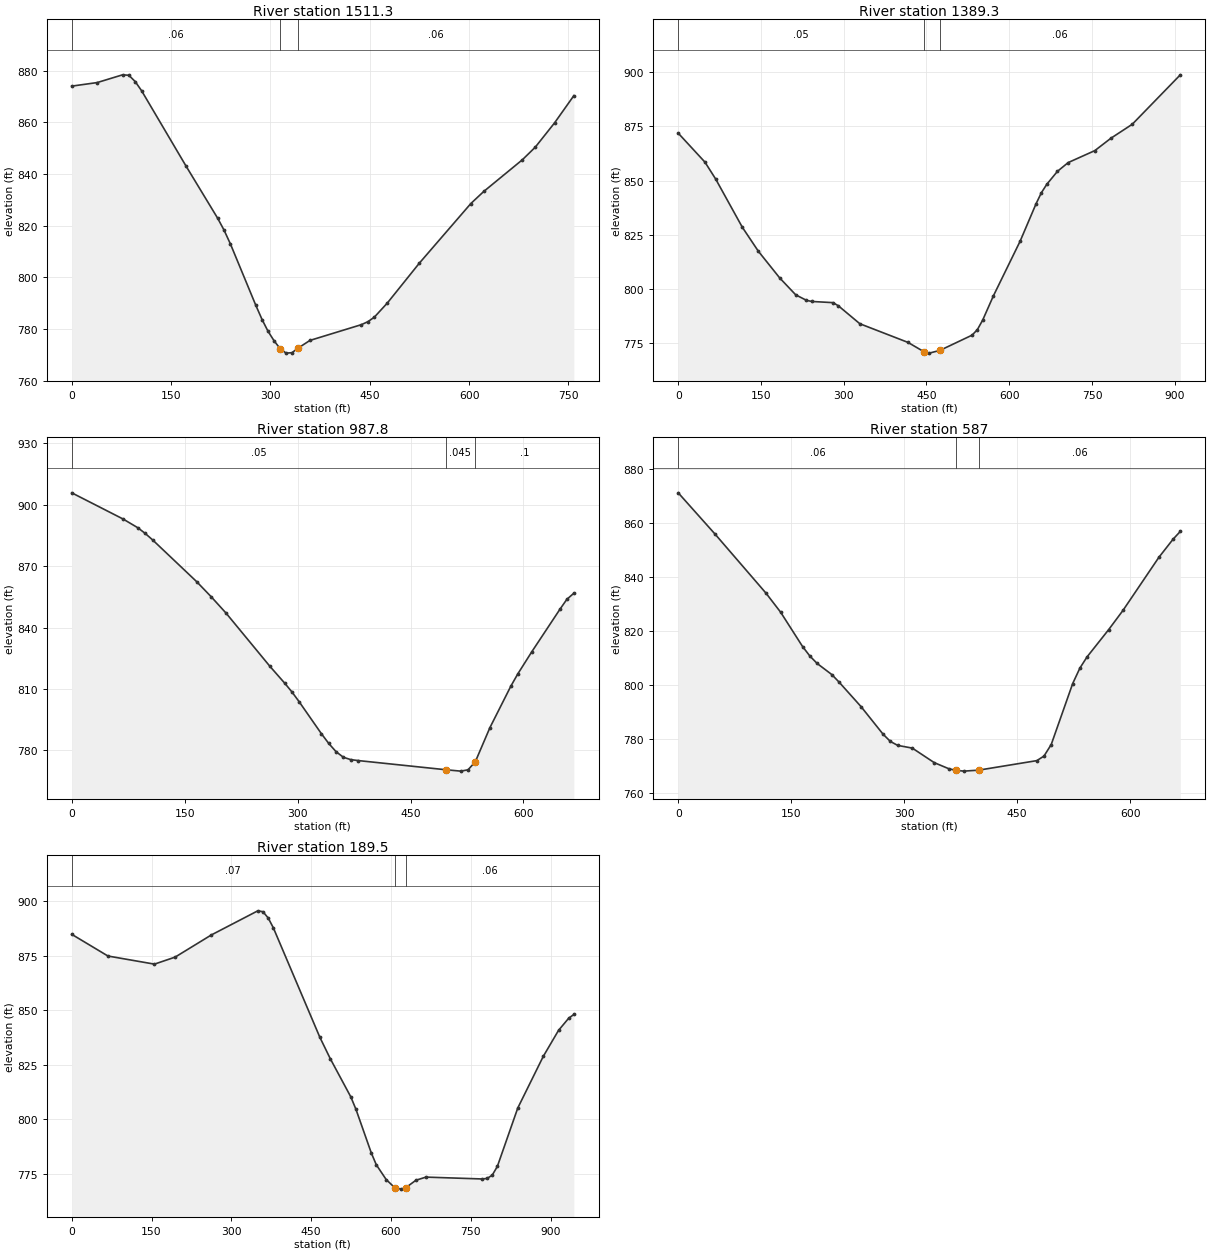
Type RM Length L Ch R = 1 ,1511.3  ,128.1,122,116.2
XS GIS Cut Line= 4
      1909912.04       620059.21      1910068.29       619817.89
     1910109.956      619758.862     1910320.026      619420.321
#Sta/Elev= 30
       0  874.03    38.3   875.4    76.7   878.4    86.2  878.23    95.8  875.79
   105.4  872.26   172.5  843.12   220.4  822.88     230  818.29   239.6  812.95
   277.9  789.24   287.5  783.65   296.5  779.12   305.6  775.46   314.6  772.49
   323.6  770.72   332.6  770.89   341.7  772.65   359.7  775.64   437.5  781.75
   447.2  782.89   456.9  784.63   476.4  790.06   524.9  805.54   602.7  828.61
   622.1  833.26   680.4  845.52   699.9  850.39     729  859.78   758.2  870.34
#Mann= 3 , 0 , 0
       0     .06       0   314.6    .045       0   341.7     .06       0
Bank Sta=314.6,341.7
XS Rating Curve= 0 ,0
Exp/Cntr=0.3,0.1

Type RM Length L Ch R = 1 ,1389.3  ,389.3,401.5,413.3
XS GIS Cut Line= 3
     1910048.348      620253.031     1910205.859      619826.051
     1910368.123      619400.998
#Sta/Elev= 30
       0  871.91    48.4  858.52    67.8  850.72   116.2  828.38   145.2   817.3
     184  804.92     213  797.12   232.4  794.59   242.1  794.06   280.8  793.51
   290.5     792   329.2  783.75   416.4  775.13   445.4  770.81   455.1  770.16
   474.5  771.44   532.6  778.47   542.2  781.01   551.9  785.46   571.3  796.66
   619.7  821.92   648.7   839.3   658.4  844.42   668.1  848.26   687.4  854.26
   706.8   858.3   755.2  863.85   784.2  869.55     823  876.03   910.1   898.9
#Mann= 3 , 0 , 0
       0     .05       0   445.4    .045       0   474.5     .06       0
Bank Sta=445.4,474.5
XS Rating Curve= 0 ,0
Exp/Cntr=0.3,0.1

Type RM Length L Ch R = 1 ,987.8   ,396.5,400.8,404.1
XS GIS Cut Line= 4
     1910158.596      620308.695      1910506.33      620010.074
     1910581.311      619948.532     1910670.286      619881.258
#Sta/Elev= 30
       0  905.75    68.3  892.94    87.8  888.69    97.5  885.95   107.3   882.8
   165.8  862.43   185.3  854.98   204.8   847.1   263.3  821.02   282.8  812.87
   292.6   808.5   302.3  803.65   331.6  788.18   341.3  783.45   351.1  779.39
   360.8  776.68   370.6  775.53   380.3  775.08   497.2  770.58   516.6  769.92
   526.3  770.55   535.2  774.15     536  774.47   555.4  791.13   583.2  811.38
   592.5   817.4   611.1  828.21   648.3  848.86   657.6  853.76   666.9  856.75
#Mann= 3 , 0 , 0
       0     .05       0   497.2    .045       0   535.2      .1       0
Bank Sta=497.2,535.2
XS Rating Curve= 0 ,0
Exp/Cntr=0.3,0.1

Type RM Length L Ch R = 1 ,587     ,411.6,397.5,383.1
XS GIS Cut Line= 4
     1910302.665      620508.428     1910600.842      620366.501
     1910694.592      620313.116     1910883.394       620184.21
#Sta/Elev= 30
       0  871.08    48.6  855.92   116.6  833.98     136  826.95   165.1  814.28
   174.8  810.76   184.5  808.01     204   803.9   213.7  801.09   242.8  792.05
     272  781.88   281.7   779.2   291.4  777.74   310.8  776.74     340  771.36
   359.6  769.08   369.5   768.5   379.3  768.23   398.9  768.59   476.2  772.11
   485.7   773.8   495.3  778.07   523.8   800.6   533.4  806.33   542.9  810.46
   571.5   820.5   590.5   827.6   638.2  847.23   657.2  853.98   666.7  856.82
#Mann= 3 , 0 , 0
       0     .06       0   369.5    .045       0   398.9     .06       0
Bank Sta=369.5,398.9
XS Rating Curve= 0 ,0
Exp/Cntr=0.3,0.1

Type RM Length L Ch R = 1 ,189.5   ,188.2,189.5,190.7
XS GIS Cut Line= 4
     1910576.862      620983.689     1910948.981      620573.605
     1910991.684      620480.434     1910937.105      620198.098
#Sta/Elev= 30
       0  884.78      68  874.84   155.4  871.12   194.3  874.34   262.3  884.49
   349.7  895.56   359.4  895.15   369.2  892.29   378.9  887.78   466.3  837.61
   485.8  827.84   524.6  810.23   534.3   804.5   563.1  784.53   572.4  779.16
     591  772.38   606.9  768.67     619  767.97   628.3   768.7   646.9  772.04
   665.8  773.48   771.3  772.63   780.8  772.87   790.4  774.38     800  778.37
   838.4  805.16   886.3  828.82     915  840.75   934.2  846.35   943.8  848.04
#Mann= 3 , 0 , 0
       0     .07       0   606.9    .045       0   628.3     .06       0
Bank Sta=606.9,628.3
XS Rating Curve= 0 ,0
Exp/Cntr=0.3,0.1

Chan Stop Cuts=-1
Use User Specified Reach Order=0
Composite Channel Slope=5